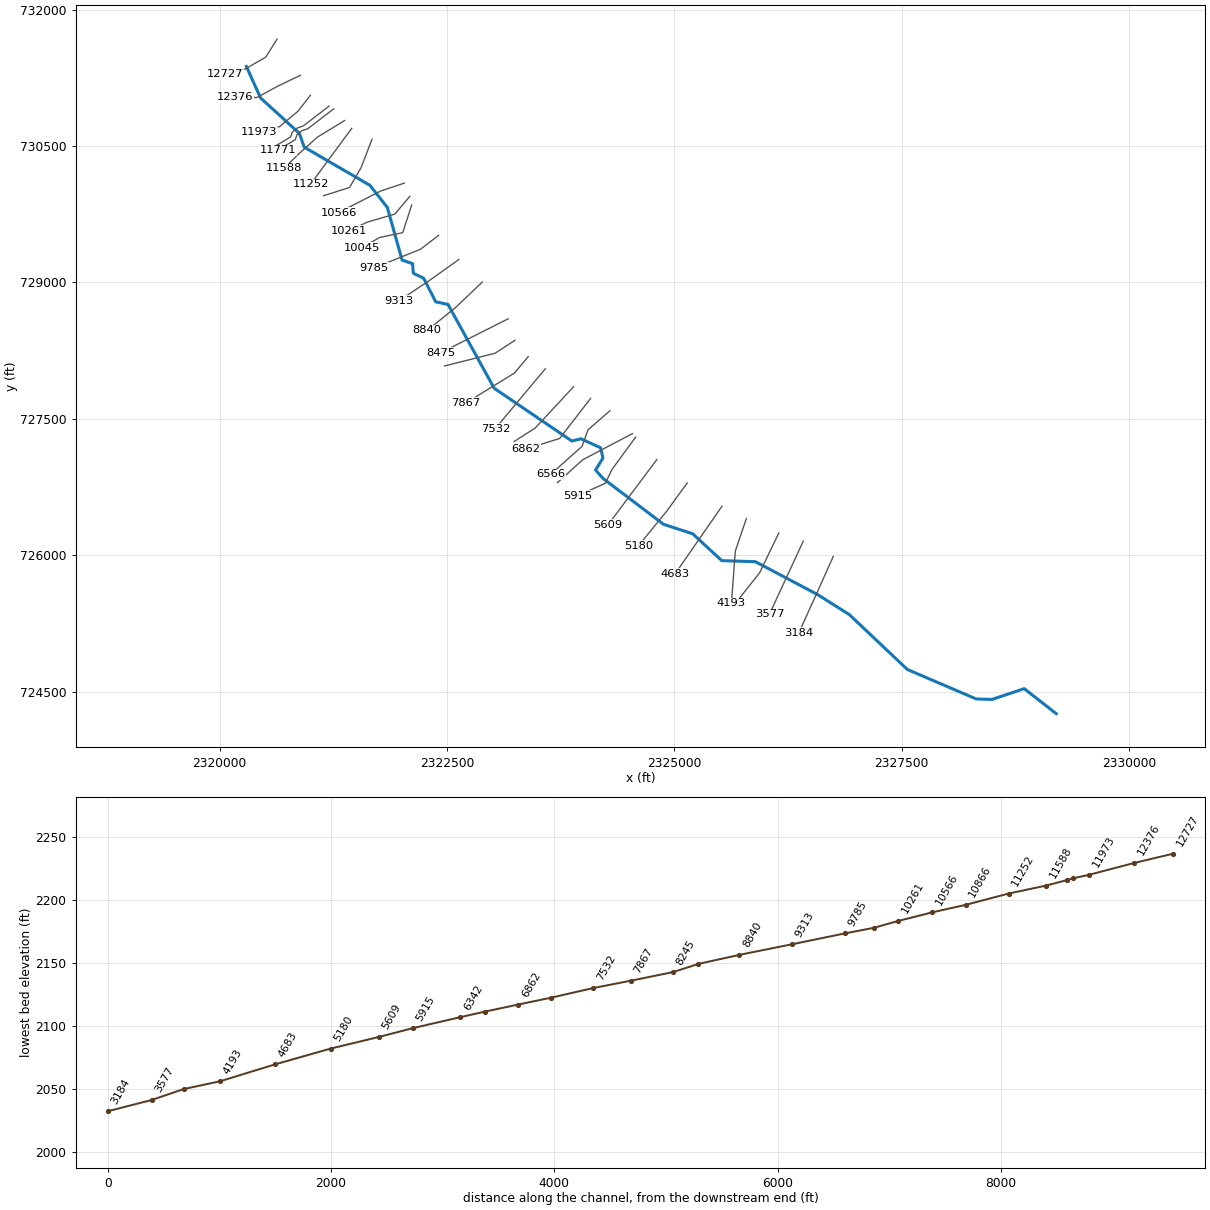
--- CLIFTONRN.prj (project) ---

Proj Title=CLIFTONRN
Current Plan=p01
Default Exp/Contr=0,0
English Units
Geom File=g01
Flow File=f01
Plan File=p01
BEGIN DESCRIPTION:
----------MODEL BY WOOD PLC 2022----------
AFH study
Randolph County, WV
HEC-RAS Version: RAS 6.2
Vertical Datum: NAVD88
Projection: NAD 1983 StatePlane West Virginia S FIPS 4702 (US Feet)
Terrain: 1-meter LIDAR (FEMA Region III 3DEP collected 2016-2018)
Land Use: 2019 NLCD
Hydrologic Method:
WV SIR2010-5033 regression equations
Additional Model Notes:
None
END DESCRIPTION:
DSS Export Rating Curves= 0
DSS Export Rating Curve Sorted= 0
DSS Export Volume Flow Curves= 0
DXF OffsetX= 0
DXF OffsetY= 0
DXF ScaleX= 0
DXF ScaleY= 0

--- CLIFTONRN.p01 (plan) ---

Plan Title=Floodplain
Program Version=6.20
Short Identifier=Floodplain
Geom File=g01
Flow File=f01
Subcritical Flow
K Sum by GR= 0
Std Step Tol= 0.01
Critical Tol= 0.01
Num of Std Step Trials= 20
Max Error Tol= 0.3
Flow Tol Ratio= 0.001
Split Flow NTrial= 30
Split Flow Tol= 0.02
Split Flow Ratio= 0.02
Log Output Level= 0
Friction Slope Method= 1
Unsteady Friction Slope Method= 2
Unsteady Bridges Friction Slope Method= 1
Parabolic Critical Depth
Global Vel Dist= 0 , 0 , 0
Global Log Level= 0
CheckData=True
Encroach Param=-1 ,0,0, 0
Mapping Interval=1HOUR
Computation Time Step Use Courant=        0
Computation Time Step Use Time Series=    0
Computation Time Step Count To Double=0
Computation Time Step Max Doubling=0
Computation Time Step Max Halving=0
Computation Time Step Residence Courant=0
Run HTab= 0
Run UNet= 0
Run Sediment= 0
Run PostProcess= 0
Run WQNet= 0
Run RASMapper=-1
UNET Theta= 0
UNET Theta Warmup= 0
UNET ZTol= 0
UNET ZSATol= 0
UNET MxIter= 0
UNET Max Iter WO Improvement= 0
UNET MaxInSteps= 0
UNET DtIC= 0
UNET DtMin= 0
UNET MaxCRTS= 0
UNET WFStab= 0
UNET SFStab= 0
UNET WFX= 1
UNET SFX= 1
UNET Gravity=32.174
UNET 1D Methodology=Finite Difference
UNET DSS MLevel= 1
UNET Pardiso=0
UNET DZMax Abort= 0
UNET Use Existing IB Tables= 0
UNET Froude Reduction=False
UNET Froude Limit= 0
UNET Froude Power= 0
UNET D1 Cores= 0
UNET WindReference=Eulerian
UNET WindDragFormulation=Hsu (1988)
UNET D2 Coriolis=0
UNET D2 Cores= 0
UNET D2 Theta= 1
UNET D2 Theta Warmup= 1
UNET D2 Z Tol= 0.01
UNET D2 Volume Tol= 0.01
UNET D2 Max Iterations= 20
UNET D2 Equation= 0
UNET D2 RampUpFraction=0.1
UNET D2 TimeSlices= 1
UNET D2 Turbulence Formulation=Non-Conservative (original)
UNET D2 Eddy Viscosity=0.3
UNET D2 Transverse Eddy Viscosity=0.1
UNET D2 Smagorinsky Mixing=0
UNET D2 BCVolumeCheck=0
UNET D2 Cores=0
UNET D2 SolverType=PARDISO (Direct)
UNET D2 Minimum Iterations= 2147483647
UNET D2 Maximum Iterations= 2147483647
UNET D2 Restart Number= 10
UNET D2 Relaxation Coeff=1.3
UNET D2 SOR Precondition Iterations= 10
UNET D2 ILUT Maximum Fill= 8
UNET D2 ILUT Tolerance=1E-08
UNET D1D2 MaxIter= 0
UNET D1D2 ZTol=0.01
UNET D1D2 QTol=0.1
UNET D1D2 MinQTol=1
Write IC File= 0
Write IC File at Fixed DateTime=0
Write IC File at Sim End=0
Echo Input=False
Echo Parameters=False
Echo Output=False
Write Detailed= 0
HDF Write Warmup=0
HDF Write Time Slices=0
HDF Flush=0
HDF Compression= 1
HDF Chunk Size= 1
HDF Spatial Parts= 1
HDF Use Max Rows=0
HDF Fixed Rows= 1
Calibration Method= 0
Calibration Iterations= 20
Calibration Max Change=0.05
Calibration Tolerance=0.2
Calibration Maximum=1.5
Calibration Minimum=0.5
Calibration Optimization Method= 1
WQ AD Non Conservative
WQ ULTIMATE=-1
WQ Max Comp Step=1HOUR
WQ Output Interval=15MIN
WQ Output Selected Increments= 0
WQ Output face flow=0
WQ Output face velocity=0
WQ Output face area=0
WQ Output face dispersion=0
WQ Output cell volume=0
WQ Output cell surface area=0
WQ Output cell continuity=0
WQ Output cumulative cell continuity=0
WQ Output face conc=0
WQ Output face dconc_dx=0
WQ Output face courant=0
WQ Output face peclet=0
WQ Output face adv mass=0
WQ Output face disp mass=0
WQ Output cell mass=0
WQ Output cell source sink temp=0
WQ Output nsm pathways=0
WQ Output nsm derived pathways=0
WQ Create Restart=0
WQ Fixed Restart=0
WQ System Summary=0
WQ Write To DSS=0
Sorting and Armoring Iterations= 10
XS Update Threshold= 0.02
Bed Roughness Predictor= 0
Hydraulics Update Threshold= 0.02
Energy Slope Method= 1
Volume Change Method= 1
Sediment Retention Method= 0
Sediment TS Multiplier= 1
Warm Up Method= 0
XS Weighting Method= 0
Number of US Weighted Cross Sections= 1
Number of DS Weighted Cross Sections= 1
Upstream XS Weight=0
Main XS Weight=1
Downstream XS Weight=0
Number of DS XS's Weighted with US Boundary= 1
Upstream Boundary Weight= 1
Weight of XSs Associated with US Boundary= 0
Number of US XS's Weighted with DS Boundary= 1
Downstream Boundary Weight= 0.5
Weight of XSs Associated with DS Boundary= 0.5
Percentile Method= 0
Sediment Output Level= 3
Mass or Volume Output= 0
Output Increment Type= 1
Profile and TS Output Increment= 1
Transport Output Increment 1
XS Output Flag= 0
XS Output Increment= 10
Read HDF5 Sediment Hotstart= 0
Sediment Hotstart Type= 0
Write Gradation File= 0
Read Gradation Hotstart= 0
Write HDF5 File= 1
Write Binary Output= 1
Write DSS Sediment File= 0
DSS Sediment Output Type= 1
SV Curve= 0
Specific Gage Flag= 0
Subcell Erosion Methods= 0
Subcell Deposition Methods= 0
Advection Scheme= 1
Matrix Solver= 0
Implicit Weighting Factor= 1
Maximum Outer Loop Convergence Iterations= 5
Convergence Maximum Absolute= 0.001
Convergence RMSE= 0.0001
Grain Fractions Max Abs Error= 0.001
Max Subgrid Regions= 1
Max Subgrid Length Scale= 3.402823E+38
Initial Layer Thickness= 3.402823E+38
Min Layer Thickness= 3.402823E+38
Max Layer Thickness= 3.402823E+38
Number of Layers= 5

--- CLIFTONRN.f01 (steady flow) ---

Flow Title=Flow
Program Version=6.20
Number of Profiles= 1
Profile Names=P100yr
River Rch & RM=CLIFTONRN,Main,12727
     386
River Rch & RM=CLIFTONRN,Main,10866
     437
River Rch & RM=CLIFTONRN,Main,9313
     491
River Rch & RM=CLIFTONRN,Main,7155
     547
River Rch & RM=CLIFTONRN,Main,4193
     614
Boundary for River Rch & Prof#=CLIFTONRN,Main            , 1
Up Type= 0
Dn Type= 3
Dn Slope=0.02329
DSS Import GetInterval= 0
DSS Import GetPeak= 0
DSS Import FillOption= 0

--- CLIFTONRN.g01 (geometry) ---

Geom Title=Geometry
Program Version=6.20

River Reach=CLIFTONRN       ,Main
Reach XY= 30
     2320294.236       731374.57     2320449.618      731029.084
     2320877.309      730638.691     2320929.393      730488.083
     2321653.698      730067.163     2321844.323      729824.455
     2322006.823      729245.809     2322121.406      729207.267
     2322130.781      729100.496      2322243.39      729046.655
     2322376.723      728786.759      2322512.14      728757.593
     2323019.258      727836.412     2323874.032      727255.813
     2323972.123      727280.9872324189.83574521727182.255906459
2324216.02834809727069.517774575     2324134.533      726937.089
     2324217.932      726843.9792324881.74868742726340.698765568
     2325203.563      726236.072     2325522.445      725940.843
     2325892.415      725929.237     2326576.131      725568.231
     2326925.579      725347.5562327564.26889092724743.967802512
      2328320.47      724420.335     2328494.997      724414.612
     2328848.711      724533.683     2329201.279      724258.518

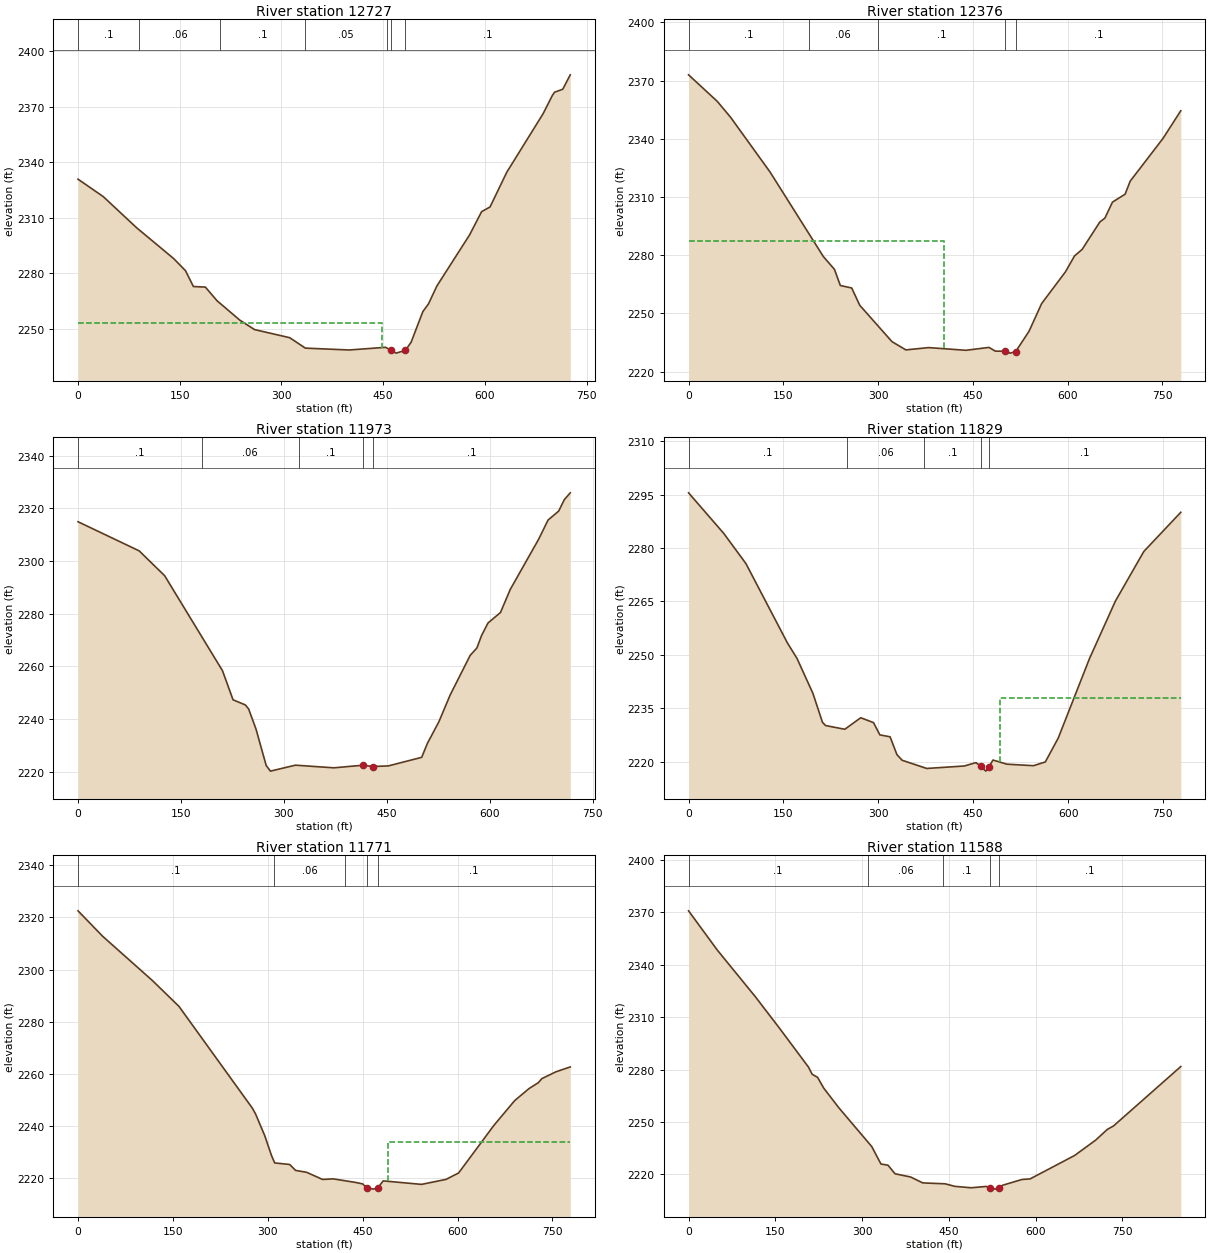
Type RM Length L Ch R = 1 ,12727   ,350.7,351.9,348.2
XS GIS Cut Line= 4
     2320631.991      731675.8812320507.10553562731476.910541887
2320284.89268679731349.0710423512320057.39588211731291.911417007
#Sta/Elev= 30
       0 2330.82    37.3 2321.39      86 2304.74   141.1 2287.96   158.5 2281.43
   170.1 2272.91   187.8 2272.59   204.9 2265.26   238.3 2254.84   260.3 2249.67
   312.1  2245.3   335.2 2239.67   399.8 2238.66   453.6 2240.11  461.592238.437
     469 2236.97   482.7 2238.48   491.1 2242.82   508.5 2259.42   516.8 2263.56
   529.1 2273.17   577.5 2300.85   595.1 2313.31   607.5 2315.83   632.2 2334.57
   685.9 2366.23   699.4    2376   702.7 2377.76   714.7 2379.33   725.8 2387.12
#Mann= 7 ,-1,0
       0      .1       0      90     .06       0     210      .1       0
  334.92     .05       0  454.92      .1       0  461.59    .045       0
   482.7      .1       0
#XS Ineff= 2 , 0
          447.65 2253.21
Permanent Ineff=
       F       F
Bank Sta=461.59,482.7
XS Rating Curve= 0 ,0
Exp/Cntr=0.3,0.1

Type RM Length L Ch R = 1 ,12376   ,400.9,402.4,404.5
XS GIS Cut Line= 4
2320888.33859689731277.8113029072320636.10714669731156.248426466
2320410.30515914731033.5083631722320167.98785288731038.797294034
#Sta/Elev= 30
       0 2372.93    45.5 2359.24    66.8 2350.94     129 2322.86   213.3 2279.35
   231.1 2272.64   240.3 2264.37   258.3 2263.09     271 2254.21     322 2235.46
   344.1 2231.18   380.1 2232.37   439.3 2230.98   475.7 2232.47   485.7 2230.55
   500.32230.482   509.3 2229.52     5182230.337   539.1  2240.8   559.1 2255.08
   596.8 2271.43   611.1  2279.6   623.2 2282.97   651.2  2297.1   659.2 2299.09
   671.2 2307.34   691.2 2311.42   699.3 2318.16   751.2 2340.15   779.4 2354.43
#Mann= 5 ,-1,0
       0      .1       0     190     .06       0     300      .1       0
   500.3    .045       0     518      .1       0
#XS Ineff= 2 , 0
          404.48 2287.15
Permanent Ineff=
       F       F
Bank Sta=500.3,518
XS Rating Curve= 0 ,0
Exp/Cntr=0.3,0.1

Type RM Length L Ch R = 1 ,11973   ,143.2,144,143.5
XS GIS Cut Line= 4
 2320997.7047014731056.7366104732320861.44895615730882.206779475
2320657.83081999730712.2698387662320435.84112266730649.500338144
#Sta/Elev= 30
       0 2314.91    89.1 2303.85   126.2 2294.42   210.5 2258.32   225.9 2247.26
   243.9 2245.29   248.6 2243.78   259.5 2236.02   274.2 2222.29   280.4 2220.15
   316.8 2222.41   372.8 2221.41   415.22222.386   429.32221.897   452.3 2222.14
   500.8 2225.39   509.1 2230.69   525.8 2238.88   542.3 2249.09   571.5 2264.16
   581.2 2266.93   588.1  2271.7   597.4 2276.43   615.6 2280.42   629.8 2289.16
   671.3  2308.3   684.9 2315.54   700.4 2318.96   708.7 2323.33   717.3  2325.9
#Mann= 5 ,-1,0
       0      .1       0     180     .06       0  321.42      .1       0
   415.2    .045       0   429.3      .1       0
Bank Sta=415.2,429.3
XS Rating Curve= 0 ,0
Exp/Cntr(USF)=0,0
Exp/Cntr=0.3,0.1

Type RM Length L Ch R = 1 ,11829   ,61.5,58.7,59.3
XS GIS Cut Line= 6
2321204.14227996730939.1139488322320916.82647146730718.707413776
2320856.20031964 730699.417274562320798.75760279730652.155809616
2320781.79549695730600.2108443082320590.11845699730485.496777823
#Sta/Elev= 30
       0 2295.54    55.6 2284.14    90.7 2275.65   156.2 2253.37   171.4    2249
   196.6 2239.17   211.7 2231.02   216.7 2230.11     247 2229.07   272.2 2232.31
   292.4 2230.94   302.4 2227.49   318.6 2226.95   329.4 2221.95   337.7 2220.35
   376.6 2218.05   435.9 2218.74   454.4 2219.69     462 2218.66     470  2217.3
  475.022218.588   481.3 2220.42   503.3 2219.25   545.3 2218.83     564 2219.88
   584.4 2226.58     634 2249.01   674.8  2265.1   719.8 2279.07   778.2 2290.07
#Mann= 5 ,-1,0
       0      .1       0     250     .06       0  372.12      .1       0
     462    .045       0  475.02      .1       0
#XS Ineff= 2 , 0
                          491.85         2237.84
Permanent Ineff=
       F       F
Bank Sta=462,475.02
XS Rating Curve= 0 ,0
Exp/Cntr=0.3,0.1

Type RM Length L Ch R = 1 ,11771   ,182.5,182.6,182.6
XS GIS Cut Line= 6
2321254.82661373  730908.85095612320967.51080523730688.444421044
2320906.88465341730669.1542818282320849.44193655730621.892816884
2320832.47983072730569.9478515762320640.80279076730455.233785091
#Sta/Elev= 30
       0 2322.52    38.7 2312.82   117.8 2295.75   159.6 2285.89   275.6 2246.88
   280.6  2244.7   295.2 2236.33   305.8 2228.78   310.9 2225.88   334.6 2225.29
     344 2223.01   361.3  2222.3   386.6 2219.55   403.4 2219.77     439  2218.4
     450 2217.84   456.1 2216.34   467.4 2215.84  474.422216.439   482.4    2219
     543 2217.66   581.8 2219.57   601.7 2222.04   657.5 2240.29   690.3 2249.77
     713 2254.38   727.6 2256.62   733.4 2258.21   755.6 2260.82   778.2 2262.68
#Mann= 5 ,-1,0
       0      .1       0     310     .06       0  422.12      .1       0
   456.1    .045       0  474.42      .1       0
#XS Ineff= 2 , 0
                          489.82         2234.03
Permanent Ineff=
       F       F
Bank Sta=456.1,474.42
XS Rating Curve= 0 ,0
Exp/Cntr=0.3,0.1

Type RM Length L Ch R = 1 ,11588   ,328.4,335.4,334
XS GIS Cut Line= 4
2321374.60651905730780.0263480392321075.16566276730597.312245416
2320873.39061767730416.3091782422320708.84040289730256.554207097
#Sta/Elev= 30
       0  2370.8    49.7 2348.34   115.3 2321.73   157.5 2303.52   207.5 2281.31
   213.7 2277.29   223.1 2275.52   233.7 2269.37   259.9 2258.09   316.8 2235.89
   332.7 2225.92   344.9 2225.24     357 2220.34   384.2 2218.47   404.9 2215.11
   443.6  2214.6   460.6 2213.14   488.8 2212.33   514.5 2213.08   521.4 2212.41
   530.7 2211.55  536.332212.394   542.8 2213.74   576.8 2217.09   590.6  2217.4
   667.4 2230.77   704.1 2239.62   723.9 2245.65     735 2247.74   851.2  2281.7
#Mann= 5 ,-1,0
       0      .1       0     310     .06       0  440.78      .1       0
   521.4    .045       0  536.33      .1       0
Bank Sta=521.4,536.33
XS Rating Curve= 0 ,0
Exp/Cntr=0.3,0.1

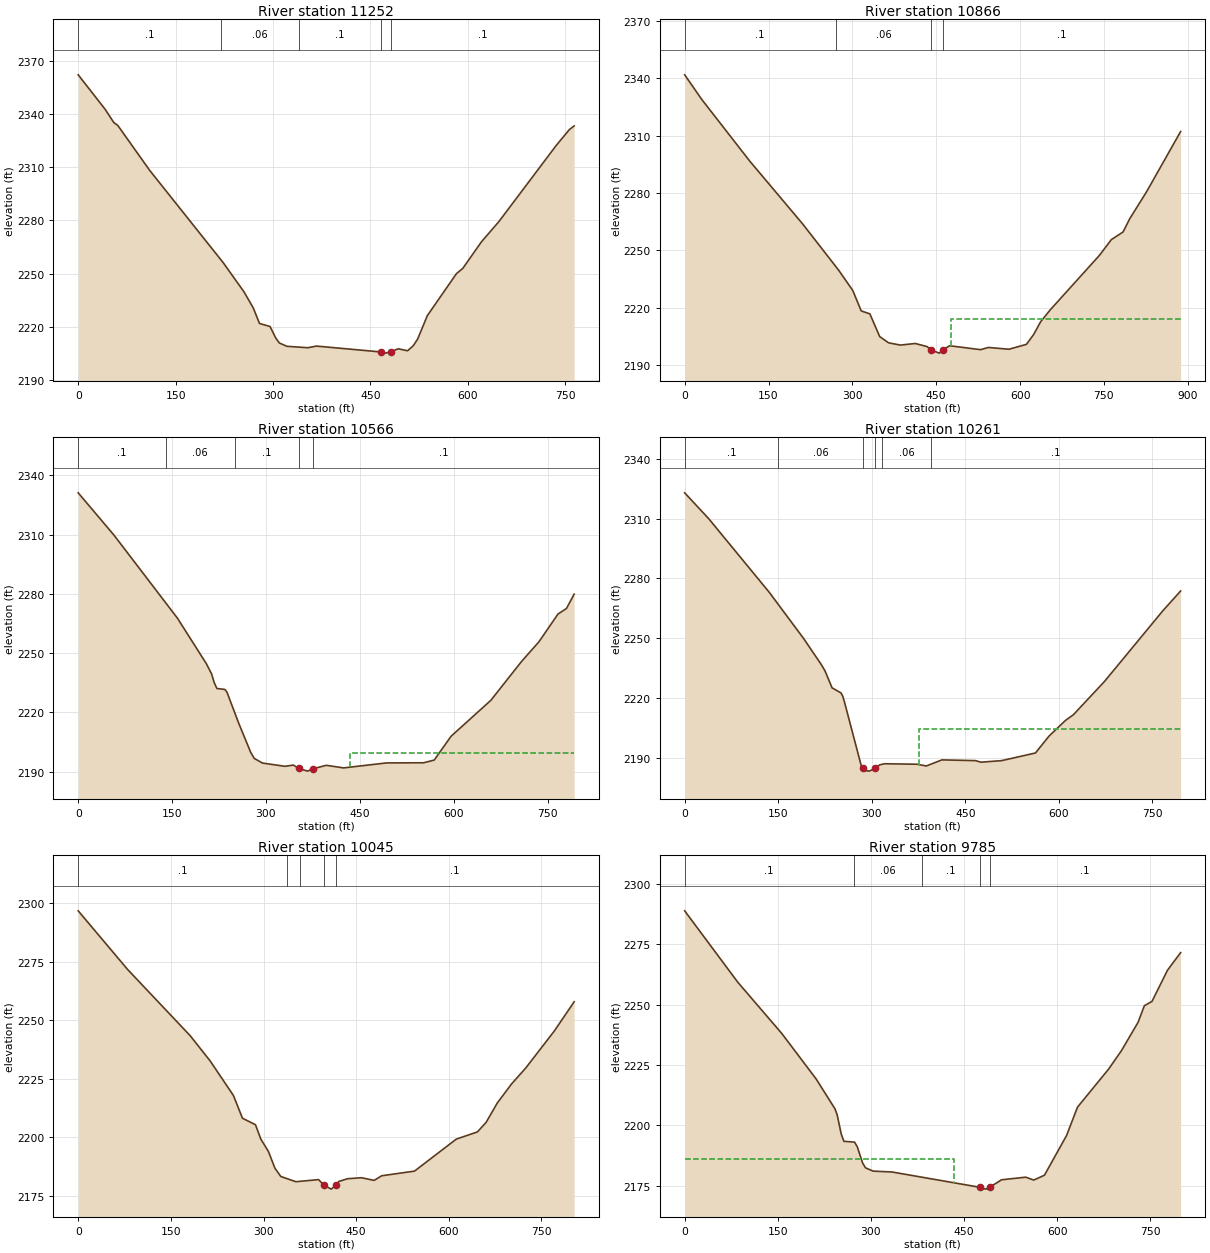
Type RM Length L Ch R = 1 ,11252   ,383.1,386.5,385.1
XS GIS Cut Line= 2
2321452.70124455730693.7629414942320999.38297298730079.234220769
#Sta/Elev= 30
       0    2362    41.3 2342.67    54.8 2335.11    60.9 2333.52   110.1 2308.16
   223.2 2256.22   255.4 2239.67   269.7 2230.57   279.1 2221.94   295.4 2220.23
   304.1 2213.78   309.7 2210.95   321.2 2209.08   353.6 2208.27   366.9  2209.2
   465.8  2205.9   472.8 2205.23   481.4 2205.99   492.8 2207.69   507.1 2206.56
   515.7 2209.32   522.6 2213.12   537.5 2226.31   582.3 2249.97   592.2    2253
   620.8  2267.9   647.8 2279.36   735.9 2322.18   756.3 2331.18   763.6 2333.23
#Mann= 5 ,-1,0
       0      .1       0     220     .06       0     340      .1       0
   465.8    .045       0   481.4      .1       0
Bank Sta=465.8,481.4
XS Rating Curve= 0 ,0
Exp/Cntr(USF)=0,0
Exp/Cntr=0.3,0.1

Type RM Length L Ch R = 1 ,10866   ,302.7,299.9,289.2
XS GIS Cut Line= 4
2321675.82015898730573.7646993742321555.92913444730262.658755736
2321429.00104633730044.037213809 2321142.1150888729953.087797198
#Sta/Elev= 30
       0 2341.74    30.6 2328.86   116.4 2296.63   210.7 2263.89     275 2239.75
   300.7 2228.97   315.8 2218.27   331.3 2216.73   348.9 2204.83   364.8 2201.58
     386  2200.4   412.6 2201.23   433.8  2199.6440.69522197.876   455.4 2196.19
  461.872197.916   473.9 2200.05   529.4    2198   543.3 2199.16   580.1 2198.22
   611.4 2200.78   624.2 2205.89   636.9 2212.66   654.2  2218.9   742.1 2247.37
   763.3 2255.56   784.3 2259.57   796.2 2266.49   826.3 2280.58   887.2 2312.08
#Mann= 4 ,-1,0
       0      .1       0     270     .06       0440.6952    .045       0
  461.87      .1       0
#XS Ineff= 2 , 0
                          477.26         2213.83
Permanent Ineff=
       F       F
Bank Sta=440.6952,461.87
XS Rating Curve= 0 ,0
Exp/Cntr=0.3,0.1

Type RM Length L Ch R = 1 ,10566   ,307.6,305.5,304.4
XS GIS Cut Line= 3
2322030.41201008730091.5714658532321770.14822702730004.816871498
 2321309.1581276729768.368075116
#Sta/Elev= 30
       0 2331.21    57.2 2309.76   158.4 2267.78   204.7 2244.68   213.2 2239.41
   217.4 2234.98   221.6 2232.08   234.3 2231.61   237.7  2230.2   256.6 2214.38
   275.5 2199.82   281.1  2196.7   294.5  2194.3   330.5 2192.66   343.7 2193.28
   352.8 2191.57   366.5 2190.22   375.5 2191.45   396.3 2193.16   424.1 2191.86
   492.7 2194.38   551.9 2194.45   568.8 2195.82   595.7 2207.87   659.2 2226.06
   708.1 2245.68   736.1 2255.73   766.6 2269.81   780.1  2272.6   792.4 2279.88
#Mann= 5 ,-1,0
       0      .1       0     140     .06       0     250      .1       0
   352.8    .045       0   375.5      .1       0
#XS Ineff= 2 , 0
                          434.62         2199.34
Permanent Ineff=
       F       F
Bank Sta=352.8,375.5
XS Rating Curve= 0 ,0
Exp/Cntr(USF)=0,0
Exp/Cntr=0.3,0.1

Type RM Length L Ch R = 1 ,10261   ,215.8,215.2,214.2
XS GIS Cut Line= 4
2322091.82792171 729946.703215342321926.64671095729751.357370341
2321625.61979407729663.5698151952321421.77444949729566.026620984
#Sta/Elev= 30
       0 2322.92    38.7  2309.9   135.8 2272.98   190.6 2249.94   219.4 2236.66
   225.1 2233.62   236.4 2225.12   250.6 2222.59   253.5 2220.96   256.3 2218.02
   283.4 2185.83   285.4 2184.76   287.6 2183.74   295.9 2183.36  305.432184.748
   312.6 2186.49   320.8 2187.06   372.5 2186.82   387.6 2185.95   412.6    2189
   466.7 2188.62   475.1 2187.84   508.4 2188.62   562.6 2192.46   584.3 2200.91
   610.9 2208.83   623.3  2211.6     673 2228.22   767.2 2263.89   795.4 2273.68
#Mann= 6 ,-1,0
       0      .1       0     150     .06       0   285.4    .045       0
  305.43      .1       0  315.82     .06       0  395.82      .1       0
#XS Ineff= 2 , 0
                          375.45         2204.28
Permanent Ineff=
       F       F
Bank Sta=285.4,305.43
XS Rating Curve= 0 ,0
Exp/Cntr=0.3,0.1

Type RM Length L Ch R = 1 ,10045   ,258.8,260.5,261.8
XS GIS Cut Line= 4
2322112.06339301729850.0194580392322013.40130531729547.228913033
2321759.94180415729494.4957282282321564.31869923729382.225076709
#Sta/Elev= 30
       0 2296.62    79.9 2271.64   181.4 2243.35   213.7 2232.59   251.3 2217.89
   265.9 2208.21     287 2205.42   295.7 2199.29     308    2194   318.5 2186.88
     328 2183.36   352.4 2181.13   389.2 2182.03   397.3 2179.73   409.6 2177.97
  417.282179.729   421.9 2181.24   436.2 2182.41   458.6 2182.83   479.1  2181.7
   491.3 2183.66   544.4 2185.65   612.1 2199.29   646.3 2202.36   660.4 2206.44
   678.5 2214.71   701.6 2222.83   724.7 2229.66   770.8 2245.39   802.9 2257.84
#Mann= 5 ,-1,0
       0      .1       0  338.46     .06       0  358.46      .1       0
   397.3    .045       0  417.28      .1       0
Bank Sta=397.3,417.28
XS Rating Curve= 0 ,0
Exp/Cntr(USF)=0,0
Exp/Cntr=0.3,0.1

Type RM Length L Ch R = 1 ,9785    ,466.3,472.2,467.1
XS GIS Cut Line= 3
2322408.04735239729517.6822380612322208.33396396729364.030356295
2321700.53142287729160.960584949
#Sta/Elev= 30
       0 2288.91    85.6 2259.29   156.3 2238.09   211.8 2219.18   242.1 2206.81
   245.6 2204.36   252.2 2196.36   256.5 2193.33   273.7 2192.99     278 2191.09
   286.6 2184.37   291.2 2182.36   303.5 2180.97     334 2180.61   476.2 2174.23
   484.8  2173.5   491.2 2174.28   510.6 2177.38   549.4 2178.45   562.3 2177.26
   579.6 2179.28   615.2 2195.75   632.8  2207.5     683  2223.3   703.6 2230.93
   730.3 2242.65   740.5 2249.56   752.8 2251.35   777.7 2264.26   798.9 2271.57
#Mann= 5 ,-1,0
       0      .1       0  271.98     .06       0  381.98      .1       0
   476.2    .045       0   491.2      .1       0
#XS Ineff= 2 , 0
          433.27 2186.18
Permanent Ineff=
       F       F
Bank Sta=476.2,491.2
XS Rating Curve= 0 ,0
Exp/Cntr=0.3,0.1

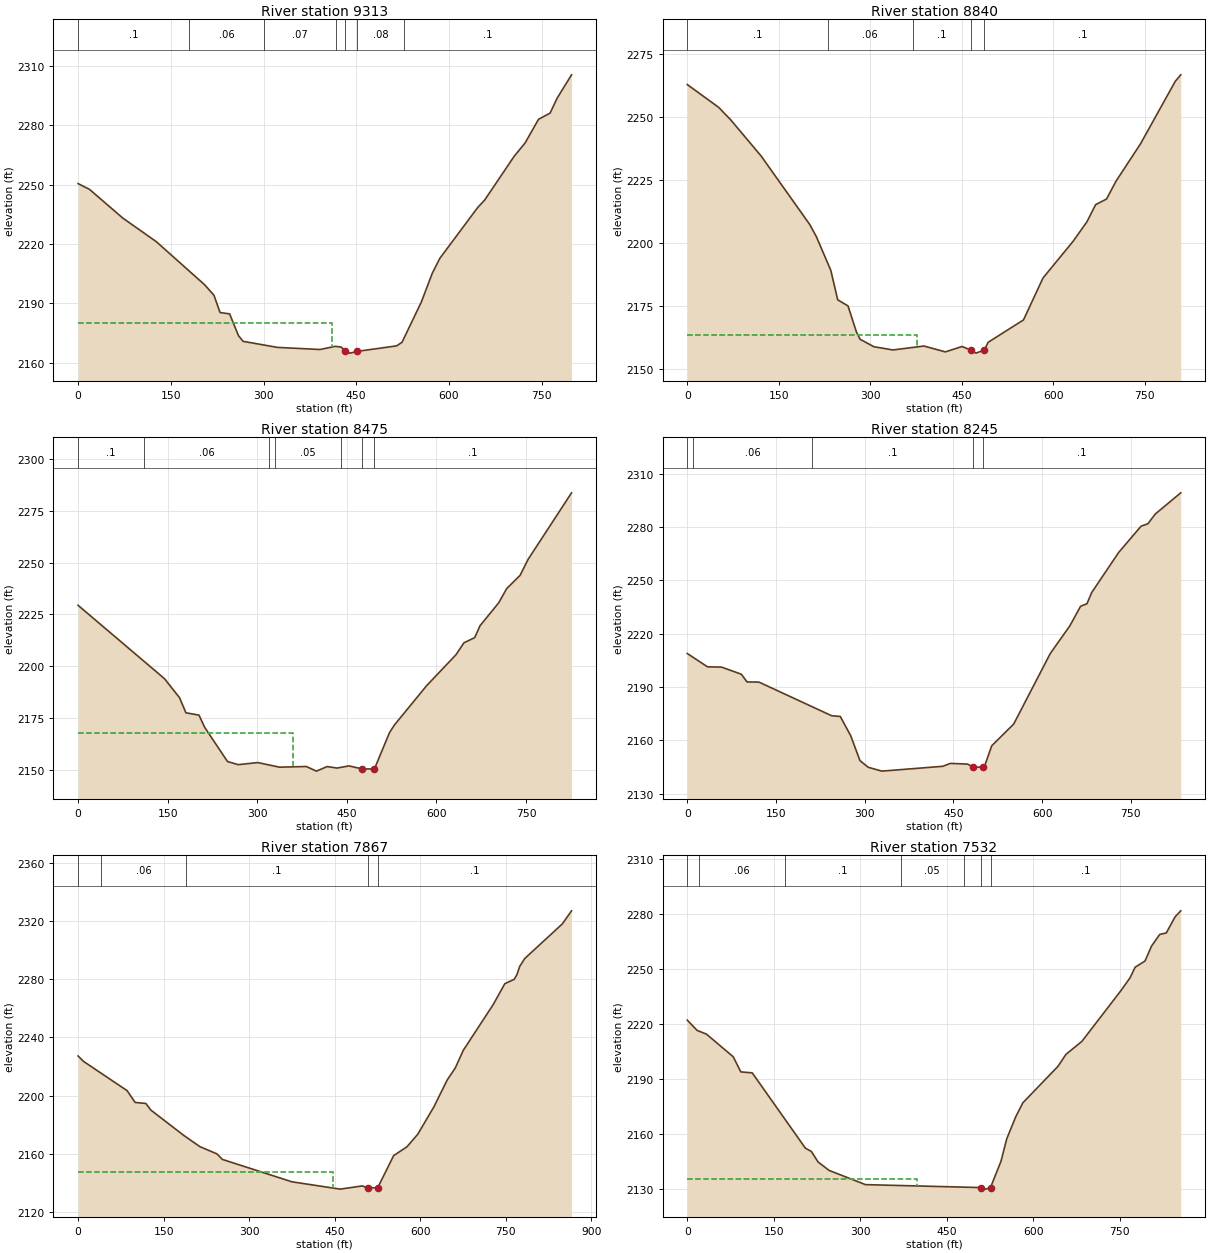
Type RM Length L Ch R = 1 ,9313    ,469.7,472.6,469.5
XS GIS Cut Line= 3
2322631.24395615729252.0630438492322290.78564761729009.545312445
2321973.49532576728799.708285817
#Sta/Elev= 30
       0 2250.61    18.5 2247.69    72.5 2233.13   126.5 2221.26   204.9 2199.41
   219.9 2194.12   229.7 2185.41   245.2 2184.73   259.5 2173.73     267 2170.84
   322.6 2167.78   391.5 2166.71   416.3 2168.32   425.9 2167.91  432.382165.752
   440.1 2164.88   451.9 2165.77   515.4 2168.55   524.1 2170.36   555.4 2190.74
   573.1 2205.26   585.4 2212.86   646.5 2238.48     658 2242.35   705.9 2264.56
   723.3 2271.16     745 2283.13   763.7 2286.25   775.2 2293.85   798.4 2305.61
#Mann= 7 ,-1,0
       0      .1       0     180     .06       0     300     .07       0
     418     .08       0  432.38    .045       0   451.9     .08       0
     528      .1       0
#XS Ineff= 2 , 0
          410.52 2180.01
Permanent Ineff=
       F       F
Bank Sta=432.38,451.9
XS Rating Curve= 0 ,0
Exp/Cntr=0.3,0.1

Type RM Length L Ch R = 1 ,8840    ,367,365.5,362.8
XS GIS Cut Line= 3
2322889.34253329729004.7615943562322590.63587236728719.717581042
2322281.16412764728471.955413458
#Sta/Elev= 30
       0 2262.89    51.4 2253.86    71.3 2248.87   121.1 2234.56   200.7 2207.46
   211.7 2202.59   235.4 2189.23   246.7 2177.56   263.6 2175.14   277.5 2164.74
   283.3 2161.94   306.1 2158.97   337.2 2157.69   388.1 2159.24   423.3 2156.92
   450.6 2159.06   464.8 2157.66   473.4 2156.43   487.4 2157.68   493.3  2160.7
   551.4 2169.59   583.4 2186.21   632.7 2200.74   655.5  2208.5   669.7 2215.28
   687.6 2217.51     703 2224.52   743.4 2239.43   800.3 2264.16   809.3 2266.74
#Mann= 5 ,-1,0
       0      .1       0     230     .06       0     370      .1       0
   464.8    .045       0   487.4      .1       0
#XS Ineff= 2 , 0
          377.48 2163.79
Permanent Ineff=
       F       F
Bank Sta=464.8,487.4
XS Rating Curve= 0 ,0
Exp/Cntr=0.3,0.1

Type RM Length L Ch R = 1 ,8475    ,231.8,229.9,227.7
XS GIS Cut Line= 2
2323173.53137101728599.7326570292322435.26678374 728228.89929292
#Sta/Elev= 30
       0 2229.44   144.8 2193.92   169.8 2184.77   180.6 2177.45   202.5 2176.32
   211.9 2170.44   250.2 2153.88   268.1 2152.37   300.9 2153.38   337.2 2151.15
     382 2151.48   399.2 2149.24   417.1 2151.45   433.4 2150.73   453.6 2151.76
     476  2150.3  494.722150.305   498.4 2151.85   521.4 2167.83   529.7 2171.58
   583.4 2190.51   632.7 2205.53   646.1 2211.32     664  2213.8     673 2219.56
   704.3 2230.67   717.7 2237.55   740.1 2243.95   753.5 2251.66   826.2 2283.84
#Mann= 7 ,-1,0
       0      .1       0     110     .06       0     320     .07       0
     330     .05       0     440      .1       0     476    .045       0
  494.72      .1       0
#XS Ineff= 2 , 0
          360.29 2167.59
Permanent Ineff=
       F       F
Bank Sta=476,494.72
XS Rating Curve= 0 ,0
Exp/Cntr(USF)=0,0
Exp/Cntr=0.3,0.1

Type RM Length L Ch R = 1 ,8245    ,375.4,377.8,380.1
XS GIS Cut Line= 3
2323248.77677525728364.2224361792323029.80609161728221.489678147
2322474.38329913728081.530127641
#Sta/Elev= 30
       0 2208.88    34.1 2201.38      58  2201.2    91.4 2197.21     101 2192.87
   121.1 2192.78   244.2 2173.83   258.6 2173.45   276.2 2162.66   291.9 2148.61
   305.8 2144.86   328.9 2142.68   432.2 2145.41   444.6 2147.03   473.8 2146.65
   483.7  2144.9   500.2 2144.97   503.5 2146.37   514.7 2156.95   551.8 2169.18
   613.7  2208.9   646.7 2224.41   664.9 2235.46   675.6 2236.87   683.8 2243.24
   729.2 2265.69   767.1  2280.5   778.7  2281.9   791.1 2287.34   834.2 2299.28
#Mann= 5 ,-1,0
       0      .1       0      10     .06       0     210      .1       0
   483.7    .045       0   500.2      .1       0
Bank Sta=483.7,500.2
XS Rating Curve= 0 ,0
Exp/Cntr=0.3,0.1

Type RM Length L Ch R = 1 ,7867    ,330.7,334.4,336.8
XS GIS Cut Line= 3
2323394.50507048728183.9282685962323241.04135629728002.253668741
2322706.48893893727673.960346888
#Sta/Elev= 30
       0 2227.27     9.8  2223.5    85.9  2203.5   100.1 2195.38   118.8 2194.69
   127.6 2190.14   185.3 2172.74   213.6 2165.03   243.5 2160.05   252.9 2156.27
     375 2140.88   459.5 2135.86   498.1 2138.06   507.4 2136.82   525.2 2136.75
   553.2 2158.84   576.6 2164.94   595.6 2173.59   623.8 2192.37   647.2 2210.84
   661.3 2219.07   675.4 2231.22   727.8 2262.61   748.1 2276.91   764.6 2279.94
   769.3 2283.08   774.3 2288.83     783 2294.18   849.1 2318.03   865.1 2326.96
#Mann= 5 ,-1,0
       0      .1       0      40     .06       0     190      .1       0
   507.4    .045       0   525.2      .1       0
#XS Ineff= 2 , 0
          447.42 2147.78
Permanent Ineff=
       F       F
Bank Sta=507.4,525.2
XS Rating Curve= 0 ,0
Exp/Cntr=0.3,0.1

Type RM Length L Ch R = 1 ,7532    ,376,377.9,376
XS GIS Cut Line= 2
2323581.78828562728050.2868927762323032.34252137727393.673688436
#Sta/Elev= 30
       0 2222.14    17.1 2216.54    33.2 2214.53    79.7 2202.18    92.8 2193.95
   112.7 2193.41   204.9 2152.39   215.3 2150.59   226.9 2144.87   246.1 2140.25
   309.2 2132.51  509.862130.905   517.8 2130.06   526.1 2130.93   544.3 2145.23
   554.3 2157.49   569.8  2169.4   582.2 2177.09     643  2196.9     657 2203.49
   684.7 2210.58   752.5 2238.26   768.2 2245.21   777.1 2250.98   794.2 2254.36
   805.5 2262.47   819.7 2268.85   831.1 2269.64   846.4 2278.44   856.2 2281.71
#Mann= 7 ,-1,0
       0      .1       0      20     .06       0     170      .1       0
     370     .05       0     480      .1       0  509.86    .045       0
   526.1      .1       0
#XS Ineff= 2 , 0
          397.74 2135.57
Permanent Ineff=
       F       F
Bank Sta=509.86,526.1
XS Rating Curve= 0 ,0
Exp/Cntr(USF)=0,0
Exp/Cntr=0.3,0.1

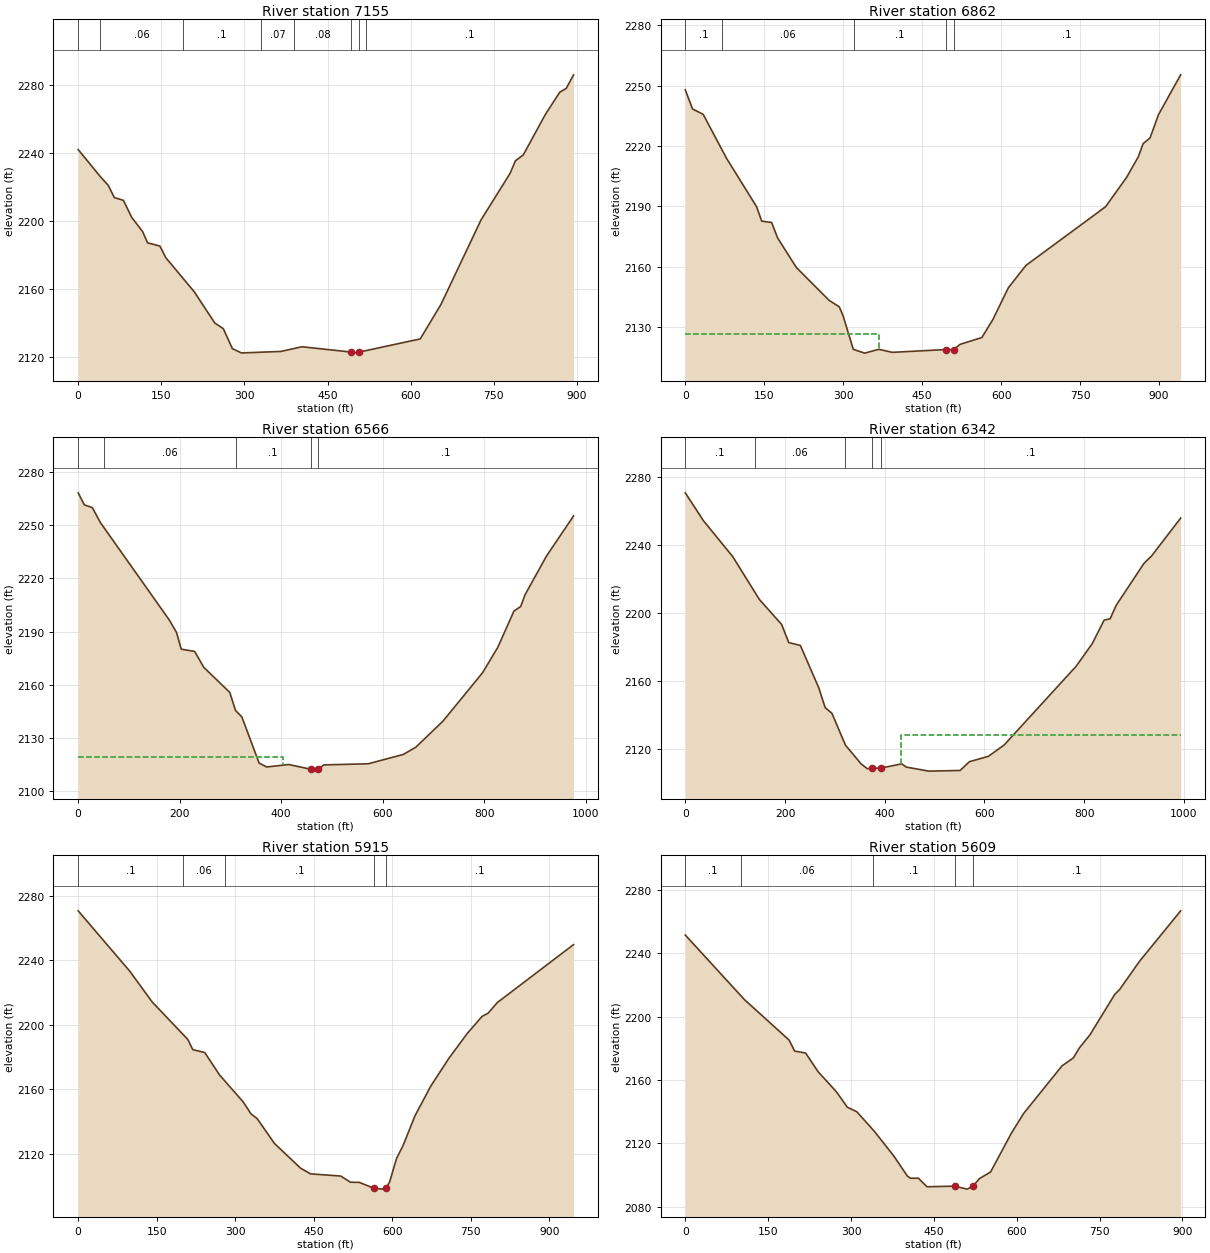
Type RM Length L Ch R = 1 ,7155    ,290.3,292.7,291.2
XS GIS Cut Line= 3
 2323892.9240549727852.9372533272323470.45344528727398.660403692
2323239.78037902727251.298836324
#Sta/Elev= 30
       0  2242.2      40 2226.28    54.3 2221.14    65.2 2213.95    81.6 2212.33
    96.6 2202.29   116.4 2193.85   125.3 2187.28   147.5  2185.4   158.1 2178.59
   209.8 2158.34   246.6 2140.07   261.9  2136.8   278.3 2125.01   294.7 2122.47
   365.7 2123.35   403.9 2126.11  493.24 2122.97   495.7 2122.36     507 2122.96
   617.4 2130.73   654.9  2151.1   727.1 2200.78   779.5 2228.17   789.2  2235.6
   803.4 2239.07   843.2 2262.89   869.3 2276.02   880.9 2278.22   894.1 2286.21
#Mann= 8 ,-1,0
       0      .1       0      40     .06       0     190      .1       0
     330     .07       0     390     .08       0  493.24    .045       0
     507     .08       0     520      .1       0
Bank Sta=493.24,507
XS Rating Curve= 0 ,0
Exp/Cntr=0.3,0.1

Type RM Length L Ch R = 1 ,6862    ,289,296.4,294.1
XS GIS Cut Line= 3
2324079.36510101 727724.089718092323739.77143227727284.731198119
2323372.20414646727168.211051664
#Sta/Elev= 30
       0 2247.96    13.8 2238.46      34 2235.78    78.5 2213.85   135.5 2189.79
   145.2 2182.63     164 2181.97   175.4 2174.26     211 2159.56   273.4 2143.16
   292.4 2140.03   299.6 2135.64   319.2 2118.81   340.8 2116.95   367.7 2118.86
     393 2117.34   494.8 2118.73  509.922118.708   521.9 2121.31   563.3  2124.7
   584.3 2133.68   613.6 2149.45     647 2160.59   798.3 2189.78     838 2204.32
   860.5 2214.65   869.6 2221.19   882.8 2224.05   898.7 2235.55   940.9 2255.44
#Mann= 5 ,-1,0
       0      .1       0      70     .06       0     320      .1       0
   494.8    .045       0  509.92      .1       0
#XS Ineff= 2 , 0
          367.77 2126.42
Permanent Ineff=
       F       F
Bank Sta=494.8,509.92
XS Rating Curve= 0 ,0
Exp/Cntr=0.3,0.1

Type RM Length L Ch R = 1 ,6566    ,230,223.8,216.8
XS GIS Cut Line= 4
2324293.18967312727589.3927860762324051.13106732727378.367334874
2323986.40477347 727198.375038262323640.60676519726889.816815493
#Sta/Elev= 30
       0 2268.12    12.2 2261.32    27.9 2259.79    43.8 2251.35   179.5 2196.49
   193.7 2189.46     203 2180.07   229.5 2178.76   247.5 2169.81   298.6 2155.72
   309.9 2145.56   322.4 2141.93   356.4 2115.93   371.3 2113.71     415 2115.08
   458.4  2112.4   466.9 2111.36  472.58 2112.39   483.9 2114.86   571.5 2115.51
   640.4 2120.74     665 2124.81   718.5 2139.46   796.6 2166.78   826.5    2181
   858.5 2201.52   871.8  2204.1   880.3 2210.69   922.7 2232.57   975.9 2255.09
#Mann= 5 ,-1,0
       0      .1       0      50     .06       0     310      .1       0
   458.4    .045       0  472.58      .1       0
#XS Ineff= 2 , 0
           402.8 2119.41
Permanent Ineff=
       F       F
Bank Sta=458.4,472.58
XS Rating Curve= 0 ,0
Exp/Cntr(USF)=0,0
Exp/Cntr=0.3,0.1

Type RM Length L Ch R = 1 ,6342    ,416.1,426.7,433.3
BEGIN DESCRIPTION:
IFA needed to wet channel
END DESCRIPTION:
XS GIS Cut Line= 3
2324540.42961708727337.8184001442323992.56152938727049.530268596
     2323715.134      726798.174
#Sta/Elev= 30
       0 2270.68    36.4 2254.28    95.2 2233.14   148.7 2207.88   193.2 2193.23
   207.5 2182.55   230.8 2180.84   267.7 2155.91   280.5 2144.27   294.1 2140.91
   321.2 2122.17   352.8 2111.09   364.9 2108.34   373.8 2108.58  391.66  2108.6
   434.2 2111.18   443.2 2109.25   488.4 2106.87   551.1 2107.26   569.8 2112.41
   607.8 2115.57   639.4 2122.24   783.9 2168.62   816.2 2181.96     840 2195.78
     852 2196.53   863.9 2204.35   919.8 2229.15   935.4 2233.62   993.4 2255.81
#Mann= 5 ,-1,0
       0      .1       0     140     .06       0     320      .1       0
   373.8    .045       0  391.66      .1       0
#XS Ineff= 2 , 0
                          433.21         2127.93
Permanent Ineff=
       F       F
Bank Sta=373.8,391.66
XS Rating Curve= 0 ,0
Exp/Cntr=0.3,0.1

Type RM Length L Ch R = 1 ,5915    ,308,305.7,303.4
XS GIS Cut Line= 4
2324575.95408564727299.3269656752324315.60599926726944.408670983
2324241.54121765726791.1421195562323935.20786526726653.686647341
#Sta/Elev= 30
       0 2270.57    98.7  2233.1   141.3 2214.11   209.3  2190.9   218.9 2184.54
   241.8 2182.75   270.1 2168.83   315.2 2152.13   330.1 2144.73   341.9 2141.81
   374.7 2126.48   424.9 2111.07   443.8 2107.57   501.5 2106.21     520  2102.4
     537 2102.28     565 2098.64   581.5 2098.11     5882098.629   594.8 2102.48
   608.1 2117.13   620.7 2125.23   643.2 2143.47   673.4 2161.91   708.3 2179.29
     743 2194.51   771.5 2205.17   782.9  2207.1   800.5  2213.7   946.2 2249.65
#Mann= 5 ,-1,0
       0      .1       0     200     .06       0     280      .1       0
     565    .045       0     588      .1       0
Bank Sta=565,588
XS Rating Curve= 0 ,0
Exp/Cntr=0.3,0.1

Type RM Length L Ch R = 1 ,5609    ,431.2,429.6,429.1
XS GIS Cut Line= 2
2324808.45377464727051.5695146152324270.91550372726333.717773082
#Sta/Elev= 30
       0 2251.52   107.2 2210.68   187.9 2185.22   197.9 2178.24   217.9 2176.98
   240.7  2165.1   273.4 2152.61   293.4 2142.77   310.5 2139.93   342.8 2127.36
   377.8 2111.85     402 2099.35   407.7 2097.92     422 2097.96   437.7 2092.54
   487.6 2092.94   510.5 2091.05     521    2093   532.7 2097.72   552.7 2101.88
   590.5 2126.44   612.6 2138.84     682 2168.88   702.6 2173.91   713.4  2180.2
   732.6 2188.47   777.5 2214.01   786.4 2217.12     822 2234.77   896.8 2266.79
#Mann= 5 ,-1,0
       0      .1       0     100     .06       0     340      .1       0
   487.6    .045       0     521      .1       0
Bank Sta=487.6,521
XS Rating Curve= 0 ,0
Exp/Cntr(USF)=0,0
Exp/Cntr=0.3,0.1

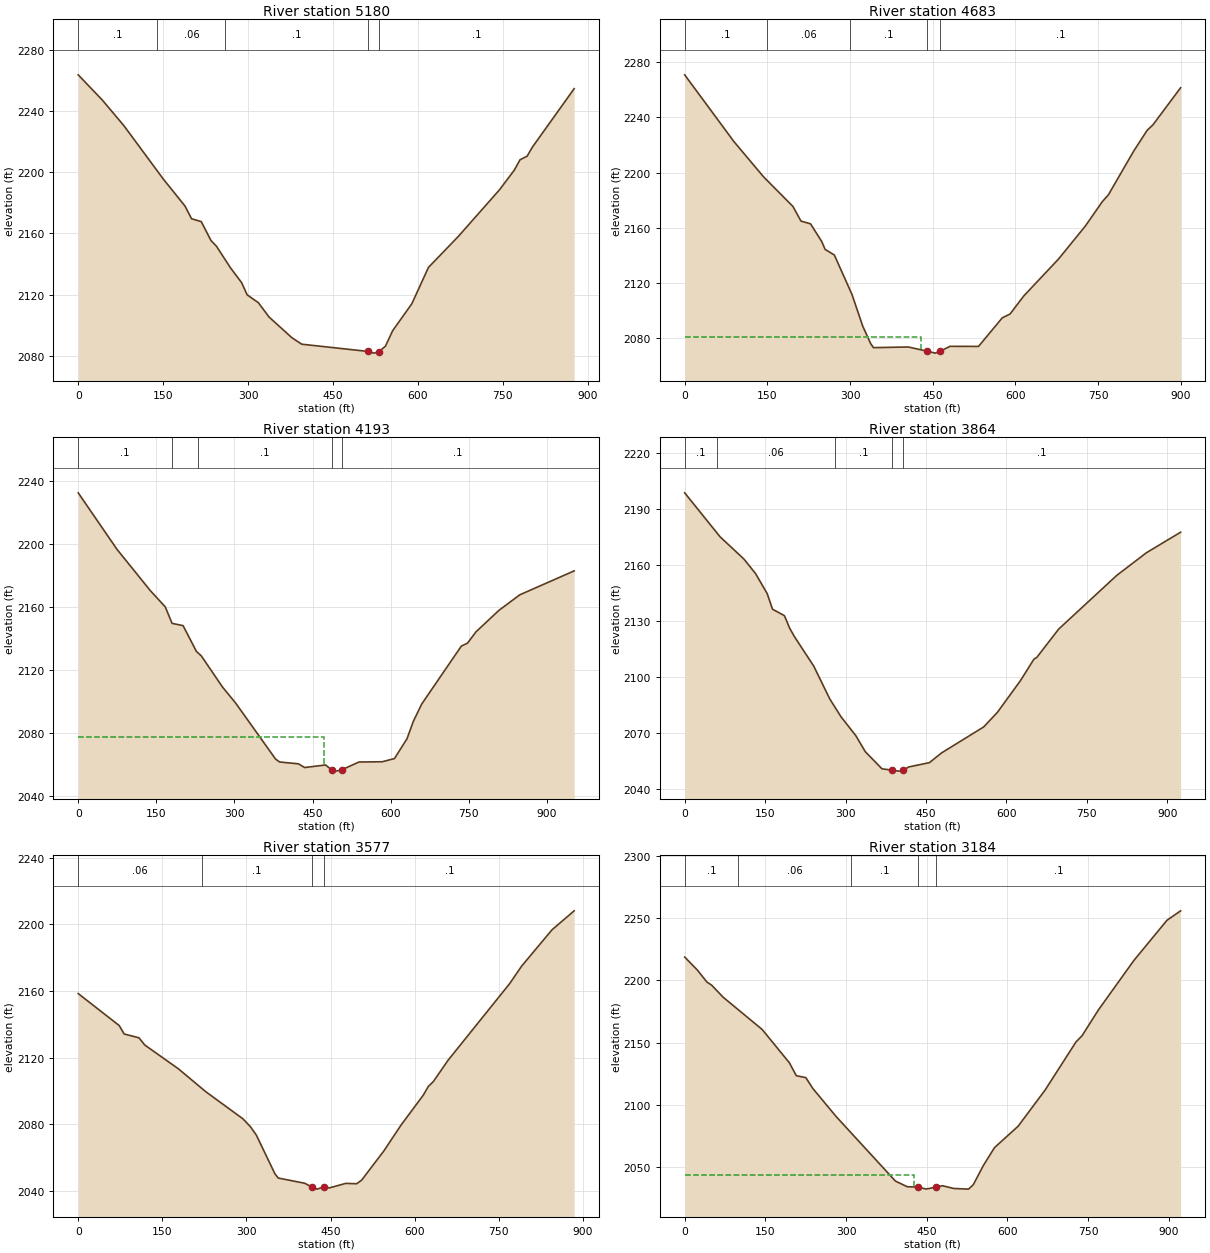
Type RM Length L Ch R = 1 ,5180    ,495.8,496.9,495.6
XS GIS Cut Line= 3
2325142.21069146 726794.668043852324915.67086669 726482.70656712
2324605.27090959 726103.23034899
#Sta/Elev= 30
       0 2263.58    42.6  2247.1    80.9 2230.28   150.1 2195.61   188.7 2177.84
   200.1 2169.63   217.3 2167.73   234.5 2155.37   244.1 2151.69   268.8 2137.63
   288.6 2127.85   298.4 2119.91   318.2 2114.78     337 2105.44   377.5 2091.87
   394.8 2087.69  512.48 2082.93   522.7 2081.86   531.2  2082.9   542.5 2086.37
   555.3 2096.51   589.1 2114.06   618.5 2137.81   671.7 2158.25   744.1 2188.57
     770 2201.29   780.3 2208.14   792.8 2210.47   801.7 2216.17   875.8 2254.53
#Mann= 5 ,-1,0
       0      .1       0     140     .06       0     260      .1       0
  512.48    .045       0   531.2      .1       0
Bank Sta=512.48,531.2
XS Rating Curve= 0 ,0
Exp/Cntr=0.3,0.1

Type RM Length L Ch R = 1 ,4683    ,481.5,489.8,491.2
XS GIS Cut Line= 2
2325524.60360785726538.515435047     2325011.861      725799.404
#Sta/Elev= 30
       0 2270.78    89.3 2222.48   142.8 2197.08   196.4 2175.49     211 2164.88
   228.3 2162.93   248.5 2150.17   254.8 2144.42   271.5 2140.35   303.5 2111.77
   322.9 2088.95   337.5 2076.13   342.4 2073.29   405.7 2073.76   439.8 2070.74
   454.4 2069.32  463.56 2070.74   481.3 2074.24     533 2074.18   576.1 2094.87
   590.2 2097.64     615 2110.66   678.3  2137.5     727 2161.43   757.2 2178.78
   768.7 2183.99   814.6 2215.65     839 2230.67   849.2 2234.47   899.6 2261.43
#Mann= 5 ,-1,0
       0      .1       0     150     .06       0     300      .1       0
   439.8    .045       0  463.56      .1       0
#XS Ineff= 2 , 0
          428.46 2080.72
Permanent Ineff=
       F       F
Bank Sta=439.8,463.56
XS Rating Curve= 0 ,0
Exp/Cntr=0.3,0.1

Type RM Length L Ch R = 1 ,4193    ,330.8,328.5,323.2
XS GIS Cut Line= 3
2325793.34852206726403.920783084     2325672.013726046.389133551
      2325629.17      725473.076
#Sta/Elev= 30
       0 2232.22    74.7 2196.34   138.7  2170.2   167.1 2160.03   180.3 2149.54
   201.4 2148.11     227 2131.79   236.5 2128.91   277.4  2109.1   302.4 2099.05
     379 2063.62   386.8 2061.75   422.9 2060.57   434.9 2058.23     475 2059.85
   487.1  2056.7   495.1 2055.95  505.67  2056.7   539.2 2061.73   583.8 2061.88
   607.4  2063.9   631.5 2076.47   643.5 2087.38   659.6 2098.38   735.8 2135.13
   747.8 2137.05   763.8 2144.12   807.7 2157.69   848.1 2167.62   952.5 2182.78
#Mann= 5 ,-1,0
       0      .1       0     180     .06       0     230      .1       0
   487.1    .045       0  505.67      .1       0
#XS Ineff= 2 , 0
          472.92 2077.59
Permanent Ineff=
       F       F
Bank Sta=487.1,505.67
XS Rating Curve= 0 ,0
Exp/Cntr=0.3,0.1

Type RM Length L Ch R = 1 ,3864    ,287.8,287.9,288.1
XS GIS Cut Line= 3
2326150.02916916726244.739044112 2325939.5186471725807.734912991
2325666.00551477 725463.13461028
#Sta/Elev= 30
       0 2198.86    66.1 2175.27   110.5 2163.36   132.2 2155.58   153.9 2144.86
   163.8 2136.47     186 2133.03   195.8 2126.31   204.8 2121.74   240.8 2105.93
   270.7 2088.34   291.7 2078.76   319.2  2068.7   336.9 2060.09     368 2050.91
   387.6 2050.17   399.1 2049.67     408 2050.14   417.6 2051.89   456.5 2054.22
     479 2059.41   557.6 2073.34   583.2 2081.15   626.2 2098.15   651.5 2109.73
   656.9 2110.68   697.7 2125.85   805.7 2154.55   861.1 2166.72     925 2177.75
#Mann= 5 ,-1,0
       0      .1       0      60     .06       0     280      .1       0
   387.6    .045       0     408      .1       0
Bank Sta=387.6,408
XS Rating Curve= 0 ,0
Exp/Cntr=0.3,0.1

Type RM Length L Ch R = 1 ,3577    ,391.6,392.8,393.7
XS GIS Cut Line= 2
2326419.38851776  726155.48338862326047.67311711725353.250151032
#Sta/Elev= 30
       0 2158.42    73.1  2139.2    81.9 2134.14   108.3 2131.85   118.6 2127.54
   178.9 2113.16   227.4 2099.49   293.5 2083.23   306.7  2078.6   317.5 2073.48
   350.6 2050.26   356.6 2047.62   403.7  2044.5  416.072042.352   425.8 2040.96
     439  2042.4   447.8  2041.7   477.1 2044.41   496.3  2044.2   505.1 2046.26
   544.8 2063.84   575.6 2079.45   615.3 2097.44   624.1  2102.6     633 2105.49
   659.4 2118.36   769.4 2164.47   790.5 2174.87   844.7 2196.71   884.2 2208.11
#Mann= 4 ,-1,0
       0     .06       0     220      .1       0  416.07    .045       0
     439      .1       0
Bank Sta=416.07,439
XS Rating Curve= 0 ,0
Exp/Cntr(USF)=0,0
Exp/Cntr=0.3,0.1

Type RM Length L Ch R = 1 ,3184    ,273.7,269,265
XS GIS Cut Line= 3
     2326748.819      725986.865      2326564.02      725574.068
     2326369.854      725146.006
#Sta/Elev= 30
       0 2218.77    23.8 2208.22    41.3 2198.66    50.1 2196.17    71.4 2186.49
     144 2160.55   194.7 2133.71   207.6 2123.29   225.4 2121.73   238.5 2112.91
   282.3 2090.14   391.9  2038.5   413.8 2033.96   434.7 2033.59   448.9 2032.09
   467.9  2033.6   479.6 2034.73   500.3 2032.56   527.9 2032.02   536.7 2035.55
   555.6 2051.13   576.2 2065.42   620.2 2082.68   670.4  2111.8   727.8 2150.51
   738.7 2155.26   769.5 2176.26   835.4 2216.03     897 2248.39   922.3 2255.96
#Mann= 5 ,-1,0
       0      .1       0     100     .06       0     310      .1       0
   434.7    .045       0   467.9      .1       0
#XS Ineff= 2 , 0
          427.29 2043.42
Permanent Ineff=
       F       F
Bank Sta=434.7,467.9
XS Rating Curve= 0 ,0
Exp/Cntr=0.3,0.1