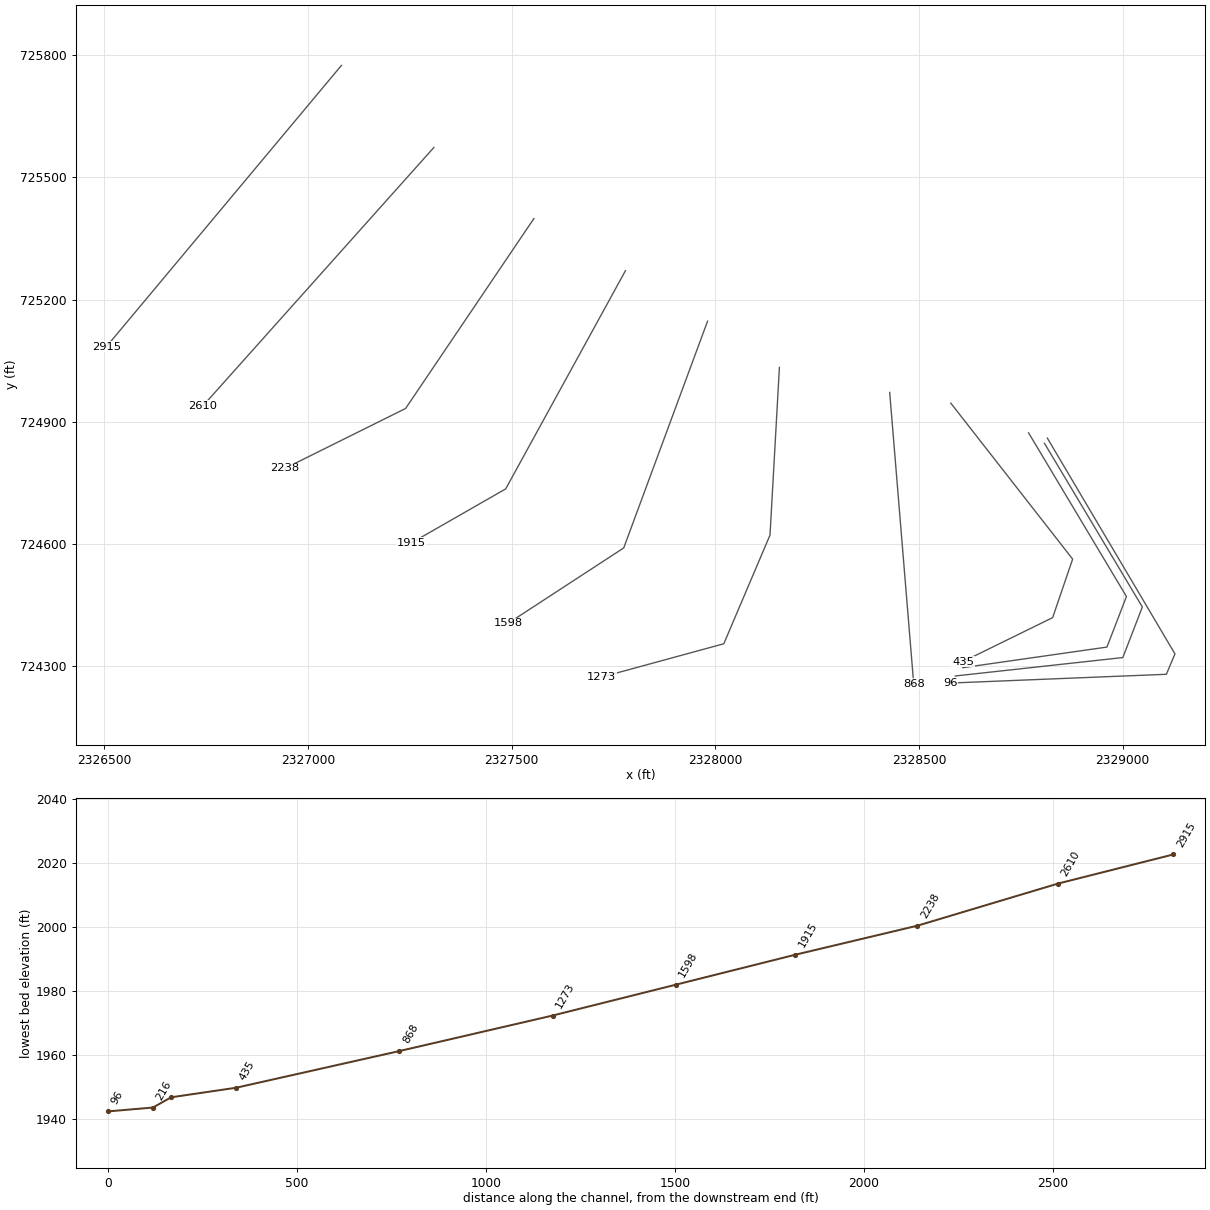
HEC-RAS study CLIFTONRN.prj: CLIFTONRN

--- CLIFTONRN.g01 (geometry) --- (continued)

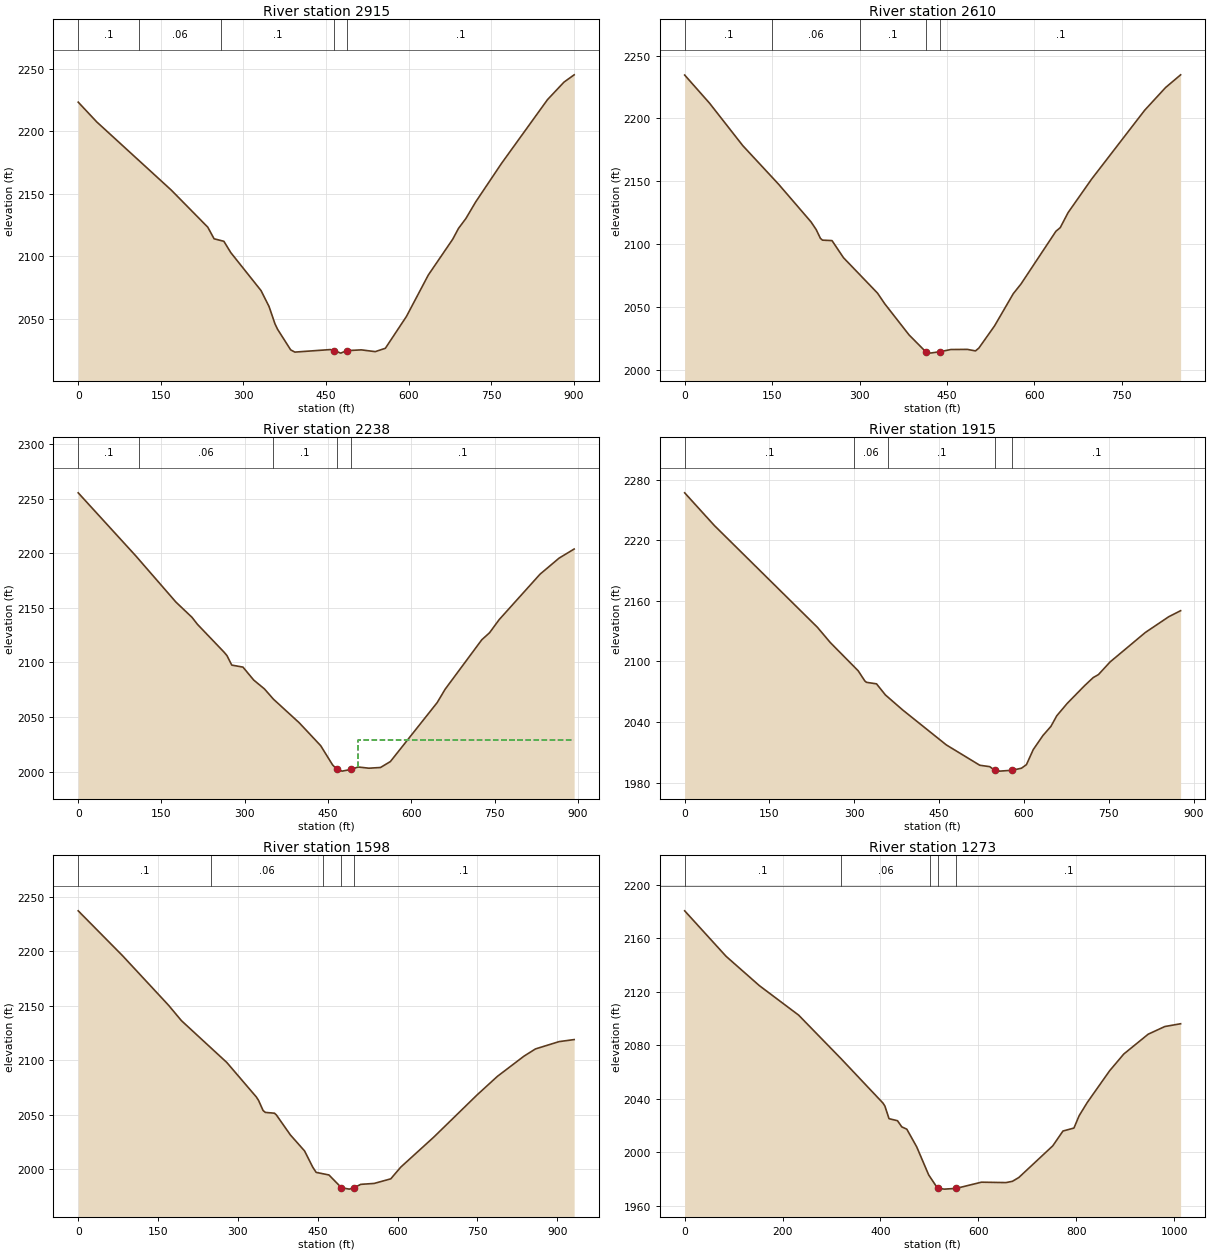
Type RM Length L Ch R = 1 ,2915    ,303.6,304.8,302.8
XS GIS Cut Line= 2
2327081.81415787725775.0020870552326504.29023031725084.073460982
#Sta/Elev= 30
       0 2223.28    33.7 2207.46   169.2  2152.9   235.3 2123.35   246.7 2114.09
   264.5 2112.08     277 2103.08   331.9 2072.74   346.5 2059.99   357.4 2045.99
   362.1 2041.71   385.8 2025.32   393.4 2023.54   457.9 2025.57   465.3 2024.66
   476.7 2022.72   487.2 2024.67     514 2025.33   539.3 2023.91   557.7 2026.58
     596 2052.05   635.7 2085.14   680.1  2113.8   690.5 2122.39   703.9 2130.28
   721.8  2143.6   768.7 2174.38   852.1 2225.28     882 2239.26   900.5 2245.11
#Mann= 5 ,-1,0
       0      .1       0     110     .06       0     260      .1       0
   465.3    .045       0   487.2      .1       0
Bank Sta=465.3,487.2
XS Rating Curve= 0 ,0
Exp/Cntr(USF)=0,0
Exp/Cntr=0.3,0.1

Type RM Length L Ch R = 1 ,2610    ,369.8,372.3,373.4
XS GIS Cut Line= 2
2327308.62355488725573.3937341582326741.60006236724939.167457337
#Sta/Elev= 30
       0 2234.47    42.7  2212.1    99.6 2178.45   161.3 2147.66   216.7 2117.86
   225.6 2111.71   232.8 2104.79   236.4 2103.34   252.7 2102.99   272.4 2089.41
   330.8 2061.26   343.2  2052.8   384.8 2028.12   413.4 2014.76   420.8 2013.61
   438.8 2014.78   456.4 2016.48   484.9 2016.58   498.8 2015.37   504.6 2017.61
   531.5 2035.22   563.7 2060.86   576.8 2068.46   636.8 2110.39   644.2 2113.27
   657.7 2125.23   697.8 2151.69     789 2206.49   824.8 2224.51   850.7 2234.65
#Mann= 5 ,-1,0
       0      .1       0     150     .06       0     300      .1       0
   413.4    .045       0   438.8      .1       0
Bank Sta=413.4,438.8
XS Rating Curve= 0 ,0
Exp/Cntr(USF)=0,0
Exp/Cntr=0.3,0.1

Type RM Length L Ch R = 1 ,2238    ,321.9,322.6,326
XS GIS Cut Line= 3
2327554.33373498725399.0865123832327239.32068358 724932.86719631
2326943.20841526724785.861105656
#Sta/Elev= 30
       0 2255.28   103.3 2197.77   176.1 2155.17   205.1 2141.19   214.7 2134.89
     263 2109.21     268 2106.17   276.6  2097.5   296.8 2095.66   316.1 2083.82
   335.4 2075.72   351.5 2066.38   398.2 2044.64   436.8 2023.69   458.1 2006.18
  465.922002.084   475.4 2000.41  492.082002.045   504.2  2004.2   523.7 2003.09
   544.5 2003.74   562.3 2009.18   646.6 2063.18   660.9 2075.41   726.9 2120.69
   740.9 2127.13   758.2 2139.12   831.8 2180.74   866.2 2195.49   893.3 2203.81
#Mann= 5 ,-1,0
       0      .1       0     110     .06       0     350      .1       0
  465.92    .045       0  492.08      .1       0
#XS Ineff= 2 , 0
                          503.25         2028.97
Permanent Ineff=
       F       F
Bank Sta=465.92,492.08
XS Rating Curve= 0 ,0
Exp/Cntr(USF)=0,0
Exp/Cntr=0.3,0.1

Type RM Length L Ch R = 1 ,1915    ,315.3,317.3,320.2
XS GIS Cut Line= 3
2327779.04304498725270.9812048132327485.03086367724735.459017431
2327254.02129264724603.153535843
#Sta/Elev= 30
       0 2266.88    52.3 2234.62   234.8 2133.72   257.6  2118.6   306.9 2090.65
   318.6 2080.63   321.6 2079.24   339.3 2077.75     355 2066.77   385.4 2051.97
   462.7  2017.3   521.9 1997.15   539.6 1995.74   548.4 1992.16   557.3 1991.33
   579.5  1992.2   595.6 1994.22   604.4 1997.72   616.5  2012.7   633.7 2026.65
   647.7 2035.61     658 2046.09   676.4  2058.3     707  2075.8   722.5 2083.94
   731.8 2086.93   752.3  2099.4   814.7  2128.6   856.2 2144.23   877.1 2150.18
#Mann= 5 ,-1,0
       0      .1       0     300     .06       0     360      .1       0
   548.4    .045       0   579.5      .1       0
Bank Sta=548.4,579.5
XS Rating Curve= 0 ,0
Exp/Cntr(USF)=0,0
Exp/Cntr=0.3,0.1

Type RM Length L Ch R = 1 ,1598    ,325.3,324.8,326.2
XS GIS Cut Line= 3
2327980.65139787725147.0760712622327774.84287096724590.553013787
 2327491.3311247724405.745356965
#Sta/Elev= 30
       0 2237.08    83.1 2196.04     170 2150.37   193.9 2136.39   279.2 2098.03
   334.7 2066.39   338.9 2063.21   347.4 2053.95   351.7 2052.25   368.8 2051.53
   372.3 2049.94   398.6 2031.63   425.3 2016.92   440.8 2001.93   447.1 1997.26
   471.1  1994.9  494.581983.202   509.3 1981.91   518.1 1983.17   530.9 1986.29
     556 1987.13   587.2 1991.33   606.1 2002.11   668.2 2029.66   749.3 2068.23
   787.5 2085.27   837.6 2103.86   859.2 2110.47   903.5 2117.16   931.8 2119.03
#Mann= 5 ,-1,0
       0      .1       0     250     .06       0     460      .1       0
  494.58    .045       0   518.1      .1       0
Bank Sta=494.58,518.1
XS Rating Curve= 0 ,0
Exp/Cntr(USF)=0,0
Exp/Cntr=0.3,0.1

Type RM Length L Ch R = 1 ,1273    ,400,405.3,413.6
XS GIS Cut Line= 4
2328157.05870666725033.6713727582328133.95774955724622.054318927
2328020.55305105724355.3432687412327720.24060871724273.439875377
#Sta/Elev= 30
       0 2180.43    84.6 2146.41   152.7 2124.45   232.9 2102.41     320 2069.67
   405.1 2036.68   409.1 2034.41   417.6 2024.96   434.9 2023.44   443.6 2018.85
   453.9 2017.12   474.1 2003.92   498.6  1982.9     517 1972.84   530.6 1972.28
   554.6 1972.82   606.4 1977.47   656.6 1977.17   669.7 1978.13   682.7 1980.94
   752.2 2004.68     773 2015.74   795.4 2017.96   806.1 2027.23   822.7 2037.12
   868.3 2060.79   897.3 2073.34   947.1 2088.15   981.1 2093.89  1013.4 2095.97
#Mann= 5 ,-1,0
       0      .1       0     320     .06       0  502.26      .1       0
     517    .045       0   554.6      .1       0
Bank Sta=517,554.6
XS Rating Curve= 0 ,0
Exp/Cntr(USF)=0,0
Exp/Cntr=0.3,0.1

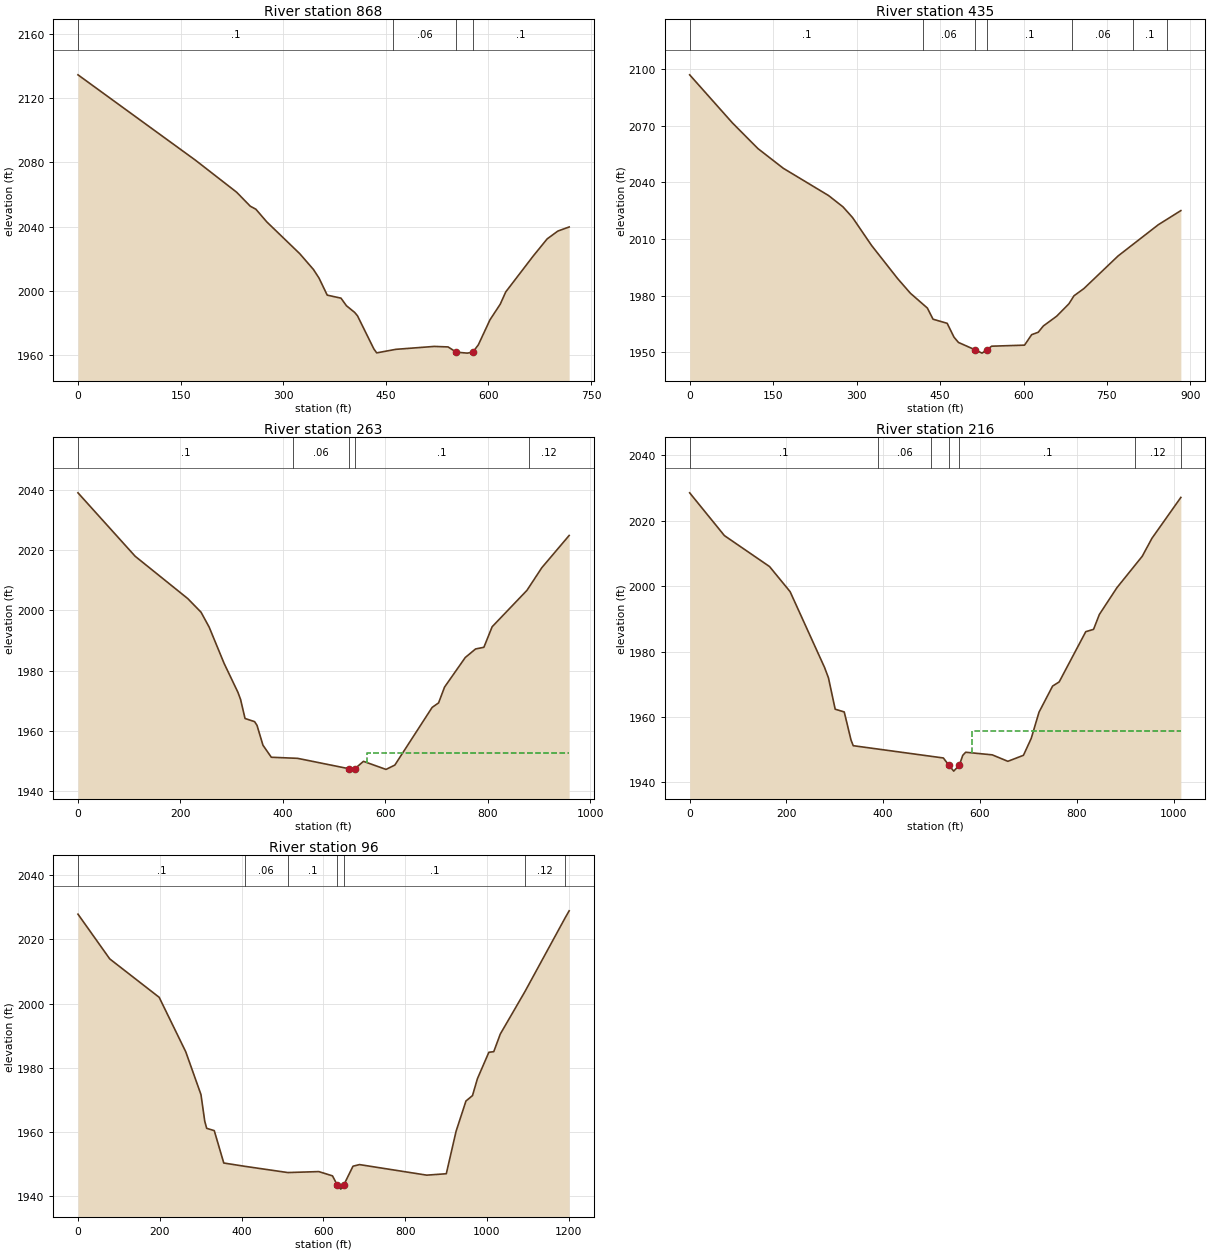
Type RM Length L Ch R = 1 ,868     ,435.5,432.3,427.5
XS GIS Cut Line= 2
2328427.82289523724972.2548253772328486.81259171724256.771151002
#Sta/Elev= 30
       0 2134.49   171.7 2081.32   231.9 2061.38   251.9 2052.65     260 2050.79
     276 2042.88   324.2 2023.07   344.2 2013.24   352.3 2007.91   364.3 1997.28
   384.4  1995.4   392.4 1990.67   404.4 1986.52   408.5 1984.43   432.5 1963.74
   436.6 1961.32   464.6 1963.52   520.8 1965.34   540.9 1965.02   552.9 1961.76
     569 1961.16     577 1961.75   585.1 1966.28   602.2 1981.93   617.2 1991.66
   625.2 1999.27   665.3  2021.6   685.8 2032.33   701.4 2037.18   717.9 2039.74
#Mann= 4 ,-1,0
       0      .1       0     460     .06       0   552.9    .045       0
     577      .1       0
Bank Sta=552.9,577
XS Rating Curve= 0 ,0
Exp/Cntr(USF)=0,0
Exp/Cntr=0.3,0.1

Type RM Length L Ch R = 1 ,435     ,172.9,171.9,167.2
XS GIS Cut Line= 4
2328577.92644093724945.8047308422328877.00718347724563.131036843
2328827.94997945 724419.523358822328607.69195008724311.449755553
#Sta/Elev= 30
       0 2096.87    76.9 2071.42   122.6 2057.88   168.3 2047.43   249.6 2033.02
   275.6 2027.02   292.7 2021.39   326.9 2006.63   373.9 1989.04   396.8 1981.31
   427.2 1973.51   437.4  1967.6   462.8 1965.43   475.1  1958.1   483.1 1955.31
   513.1  1951.4   525.4 1949.66   534.2 1951.39   542.7 1953.33   601.9 1953.88
   614.6 1959.42   626.5 1960.71   635.7 1964.04   659.5 1969.16   681.7 1975.78
   690.7 1979.99   708.5  1983.8   769.9 2001.04   842.1 2017.54   882.8 2025.05
#Mann= 7 ,-1,0
       0      .1       0     420     .06       0   513.1    .045       0
   534.2      .1       0  687.44     .06       0  797.44      .1       0
  857.44     .12       0
Bank Sta=513.1,534.2
XS Rating Curve= 0 ,0
Exp/Cntr(USF)=0,0
Exp/Cntr=0.3,0.1

Type RM Length L Ch R = 1 ,263     ,48.5,47.8,53.4
XS GIS Cut Line= 4
2328768.83694453724872.9827730542329009.12222721724471.325086521
2328961.24250298724347.1924681672328607.46454067724296.652759265
#Sta/Elev= 30
       0 2038.97   111.6 2017.93   214.2  2003.9   240.2 1999.37     256 1994.43
   285.2 1982.39   312.1 1972.82   317.3 1970.45     326 1964.13   344.7 1963.08
   349.4 1961.84     361 1955.26   377.3 1951.27   428.6 1950.91  529.57 1947.44
   534.7 1946.67   539.9 1947.41   557.1 1949.91   601.1 1947.24   618.3 1948.67
   691.1  1967.8   703.7  1969.3   715.3 1974.53   755.8 1984.36   775.9 1987.19
   792.1 1987.74   808.2 1994.55   876.1 2006.62   905.2 2014.15   958.5 2024.83
#Mann= 5 ,-1,0
       0      .1       0     420     .06       0  529.57    .045       0
   539.9      .1       0  881.09     .12       0
#XS Ineff= 2 , 0
                          563.49         1952.76
Permanent Ineff=
       F       F
Bank Sta=529.57,539.9
XS Rating Curve= 0 ,0
Exp/Cntr(USF)=0,0
Exp/Cntr=0.3,0.1

Type RM Length L Ch R = 1 ,216     ,119.4,119.6,117.7
XS GIS Cut Line= 4
2328807.85005316724847.2695878232329048.13533583 724445.61190129
2329000.25561161724321.4792829362328588.84464792724276.259543393
#Sta/Elev= 30
       0 2028.49    71.8 2015.42   165.1 2005.96   207.5 1998.31   278.8 1975.12
   286.8 1971.95   300.7 1962.39   319.4 1961.55   333.4 1952.98     338 1951.24
   524.2 1947.49  535.87 1945.24   545.6 1943.47   557.21945.265   564.3 1948.29
   570.4 1949.24   625.3 1948.44   657.5 1946.47   689.7  1948.3   705.8 1953.47
   721.9 1961.48     750 1969.46   763.6 1970.73   818.5 1986.07   834.6 1986.78
   846.6 1991.33   882.9 1999.51   935.2 2009.11   955.3 2014.61    1015 2027.09
#Mann= 7 ,-1,0
       0      .1       0     390     .06       0  498.04      .1       0
  535.87    .045       0   557.2      .1       0  921.09     .12       0
 1014.98      .1       0
#XS Ineff= 2 , 0
                          583.64         1955.76
Permanent Ineff=
       F       F
Bank Sta=535.87,557.2
XS Rating Curve= 0 ,0
Exp/Cntr(USF)=0,0
Exp/Cntr=0.3,0.1

Type RM Length L Ch R = 1 ,96      ,19.4,19.4,19.4
BEGIN DESCRIPTION:
Area disconnected without IFA
END DESCRIPTION:
XS GIS Cut Line= 4
 2328814.9229598724860.0883383242329128.23077574  724330.4322989
2329107.11589783724280.4081550012328575.91142736724258.852236106
#Sta/Elev= 30
       0 2027.87    77.7 2013.94   198.6 2001.98   263.6 1985.02   300.8  1971.7
   310.1 1963.37   314.8 1961.18   333.3 1960.47   356.6 1950.38   407.7 1949.36
   513.1 1947.41     589 1947.71   622.5 1946.38   634.1 1943.55   642.8 1942.25
  650.13 1943.56   672.6 1949.39   688.6 1949.89     853  1946.6   900.8 1947.04
   924.8 1960.29   948.9 1969.69   964.9 1971.38   976.9 1976.63  1004.9 1984.86
  1016.9 1985.06  1032.9 1990.55    1093 2003.73  1191.1 2026.64  1201.3 2028.91
#Mann= 7 ,-1,0
       0      .1       0   407.7     .06       0   513.1      .1       0
   634.1    .045       0  650.13      .1       0    1093     .12       0
  1191.1      .1       0
Bank Sta=634.1,650.13
XS Rating Curve= 0 ,0
Exp/Cntr(USF)=0,0
Exp/Cntr=0.3,0.1
LCMann Table=0

Chan Stop Cuts=-1
Use User Specified Reach Order=0
Composite Channel Slope=5